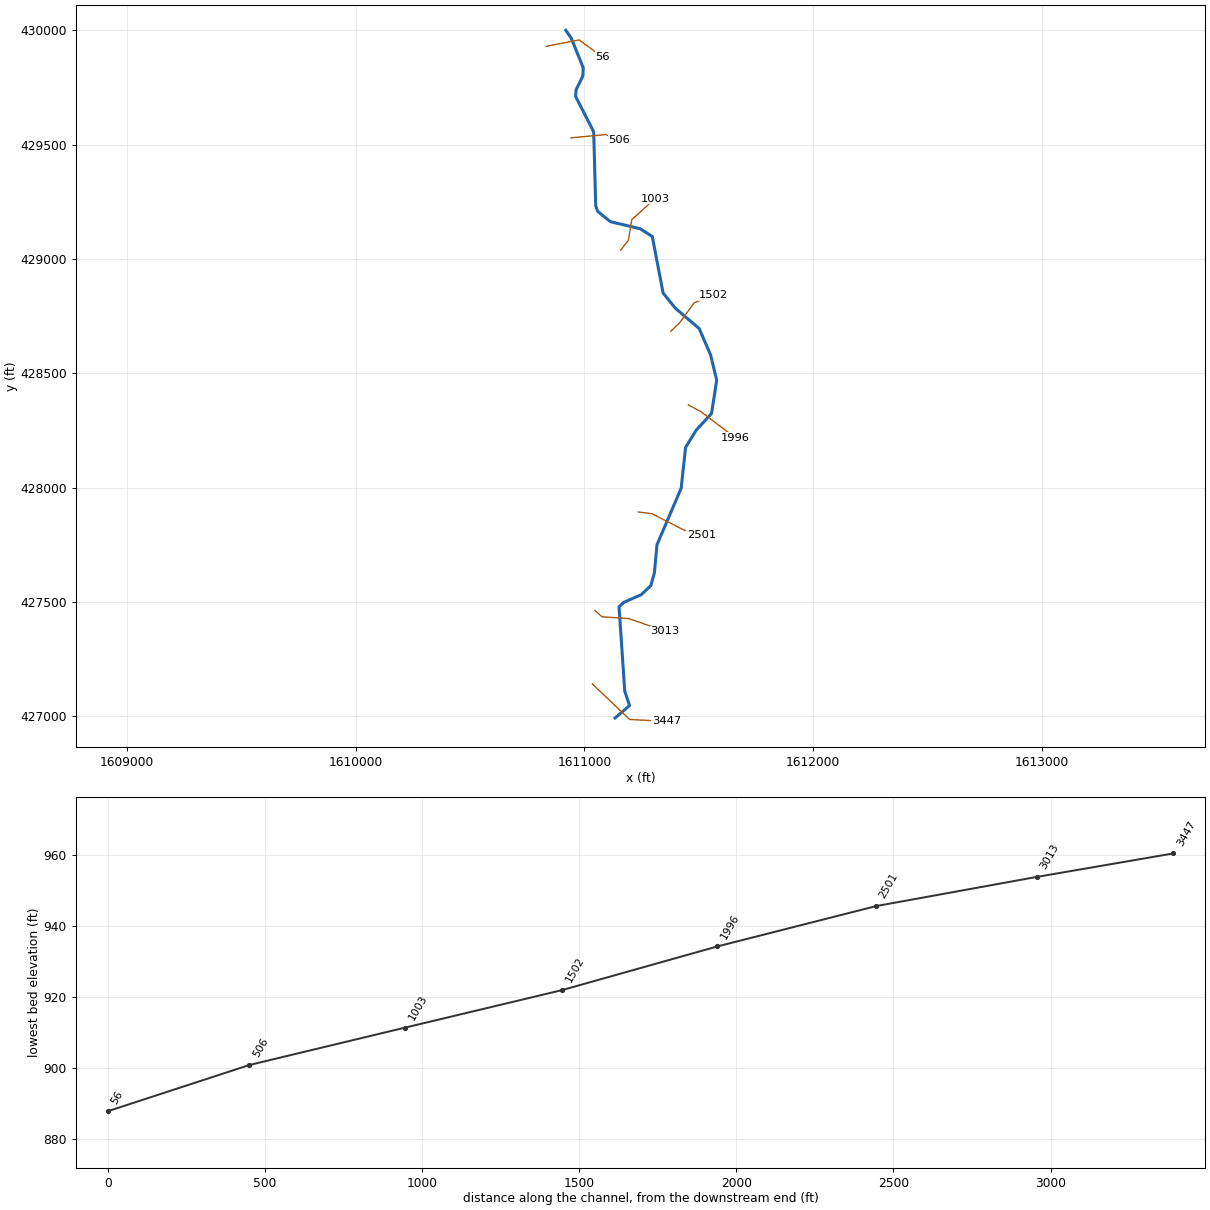
--- MCCLDRN.prj (project) ---

Proj Title=MCCLDRN
Current Plan=p01
Default Exp/Contr=0,0
English Units
Geom File=g01
Flow File=f01
Plan File=p01
BEGIN DESCRIPTION:
---------- MODELED AS PART OF WVEMD CTP PROGRAM, 2023----------
Stream Name: McCloud Run
Flood Zone:  AFH
Wetzel County, WV
HEC-RAS Version: RAS 6.3
Vertical Datum: NAVD88
Projection: NAD 1983 StatePlane West Virginia S FIPS 4702 (US Feet)
Terrain: 1-meter West Virginia FEMA R3 South Central (collected 2018-2020)
Land Use: 2019 NLCD
Hydrologic Method:
WV SIR2010-5033 regression equations
Additional Model Notes:
None
END DESCRIPTION:
DSS Export Rating Curves= 0
DSS Export Rating Curve Sorted= 0
DSS Export Volume Flow Curves= 0
DXF OffsetX= 0
DXF OffsetY= 0
DXF ScaleX= 0
DXF ScaleY= 0

--- MCCLDRN.p01 (plan) ---

Plan Title=Floodplain
Program Version=6.30
Short Identifier=Floodplain
Geom File=g01
Flow File=f01
Subcritical Flow
K Sum by GR= 0
Std Step Tol= 0.01
Critical Tol= 0.01
Num of Std Step Trials= 20
Max Error Tol= 0.3
Flow Tol Ratio= 0.001
Split Flow NTrial= 30
Split Flow Tol= 0.02
Split Flow Ratio= 0.02
Log Output Level= 0
Friction Slope Method= 1
Unsteady Friction Slope Method= 2
Unsteady Bridges Friction Slope Method= 1
Parabolic Critical Depth
Global Vel Dist= 0 , 0 , 0
Global Log Level= 0
CheckData=True
Encroach Param=-1 ,0,0, 0
Mapping Interval=1HOUR
Computation Time Step Use Courant=        0
Computation Time Step Use Time Series=    0
Computation Time Step Count To Double=0
Computation Time Step Max Doubling=0
Computation Time Step Max Halving=0
Computation Time Step Residence Courant=0
Run HTab= 0
Run UNet= 0
Run Sediment= 0
Run PostProcess= 0
Run WQNet= 0
Run RASMapper=-1
UNET Theta= 0
UNET Theta Warmup= 0
UNET ZTol= 0
UNET ZSATol= 0
UNET MxIter= 0
UNET Max Iter WO Improvement= 0
UNET MaxInSteps= 0
UNET DtIC= 0
UNET DtMin= 0
UNET MaxCRTS= 0
UNET WFStab= 0
UNET SFStab= 0
UNET WFX= 1
UNET SFX= 1
UNET Gravity=32.17405
UNET 1D Methodology=Finite Difference
UNET DSS MLevel= 1
UNET Pardiso=0
UNET DZMax Abort= 0
UNET Use Existing IB Tables= 0
UNET Froude Reduction=False
UNET Froude Limit= 0
UNET Froude Power= 0
UNET D1 Cores= 0
UNET WindReference=Eulerian
UNET WindDragFormulation=Hsu (1988)
UNET D2 Coriolis=0
UNET D2 Cores= 0
UNET D2 Theta= 1
UNET D2 Theta Warmup= 1
UNET D2 Z Tol= 0.01
UNET D2 Volume Tol= 0.01
UNET D2 Max Iterations= 20
UNET D2 Equation= 0
UNET D2 RampUpFraction=0.1
UNET D2 TimeSlices= 1
UNET D2 Turbulence Formulation=Non-Conservative (original)
UNET D2 Eddy Viscosity=0.3
UNET D2 Transverse Eddy Viscosity=0.1
UNET D2 Smagorinsky Mixing=0
UNET D2 BCVolumeCheck=0
UNET D2 Cores=0
UNET D2 SolverType=PARDISO (Direct)
UNET D2 Minimum Iterations= 3
UNET D2 Maximum Iterations= 30
UNET D2 Restart Number= 10
UNET D2 Relaxation Coeff=1.3
UNET D2 SOR Precondition Iterations= 10
UNET D2 ILUT Maximum Fill= 8
UNET D2 ILUT Tolerance=1E-08
UNET D2 Convergence Tolerance=0.00001
UNET D1D2 MaxIter= 0
UNET D1D2 ZTol=0.01
UNET D1D2 QTol=0.1
UNET D1D2 MinQTol=1
Write IC File= 0
Write IC File at Fixed DateTime=0
Write IC File at Sim End=0
Echo Input=False
Echo Parameters=False
Echo Output=False
Write Detailed= 0
HDF Write Warmup=0
HDF Write Time Slices=0
HDF Flush=0
HDF Compression= 1
HDF Chunk Size= 1
HDF Spatial Parts= 1
HDF Use Max Rows=0
HDF Fixed Rows= 1
Calibration Method= 0
Calibration Iterations= 20
Calibration Max Change=0.05
Calibration Tolerance=0.2
Calibration Maximum=1.5
Calibration Minimum=0.5
Calibration Optimization Method= 1
WQ AD Non Conservative
WQ ULTIMATE=-1
WQ Max Comp Step=1HOUR
WQ Output Interval=15MIN
WQ Output Selected Increments= 0
WQ Output face flow=0
WQ Output face velocity=0
WQ Output face area=0
WQ Output face dispersion=0
WQ Output cell volume=0
WQ Output cell surface area=0
WQ Output cell continuity=0
WQ Output cumulative cell continuity=0
WQ Output face conc=0
WQ Output face dconc_dx=0
WQ Output face courant=0
WQ Output face peclet=0
WQ Output face adv mass=0
WQ Output face disp mass=0
WQ Output cell mass=0
WQ Output cell source sink temp=0
WQ Output nsm pathways=0
WQ Output nsm derived pathways=0
WQ Create Restart=0
WQ Fixed Restart=0
WQ System Summary=0
WQ Write To DSS=0
Sorting and Armoring Iterations= 10
XS Update Threshold= 0.02
Bed Roughness Predictor= 0
Hydraulics Update Threshold= 0.02
Energy Slope Method= 1
Volume Change Method= 1
Sediment Retention Method= 0
Sediment TS Multiplier= 1
Warm Up Method= 0
XS Weighting Method= 0
Number of US Weighted Cross Sections= 1
Number of DS Weighted Cross Sections= 1
Upstream XS Weight=0
Main XS Weight=1
Downstream XS Weight=0
Number of DS XS's Weighted with US Boundary= 1
Upstream Boundary Weight= 1
Weight of XSs Associated with US Boundary= 0
Number of US XS's Weighted with DS Boundary= 1
Downstream Boundary Weight= 0.5
Weight of XSs Associated with DS Boundary= 0.5
Percentile Method= 0
Sediment Output Level= 3
Mass or Volume Output= 0
Output Increment Type= 1
Profile and TS Output Increment= 1
Transport Output Increment 1
XS Output Flag= 0
XS Output Increment= 10
Read HDF5 Sediment Hotstart= 0
Sediment Hotstart Type= 0
Write Gradation File= 0
Read Gradation Hotstart= 0
Write HDF5 File= 1
Write Binary Output= 1
Write DSS Sediment File= 0
DSS Sediment Output Type= 1
SV Curve= 0
Specific Gage Flag= 0
Subcell Erosion Methods= 0
Subcell Deposition Methods= 0
Advection Scheme= 1
Matrix Solver= 0
Implicit Weighting Factor= 1
Maximum Outer Loop Convergence Iterations= 5
Convergence Maximum Absolute= 0.001
Convergence RMSE= 0.0001
Grain Fractions Max Abs Error= 0.001
Max Subgrid Regions= 1
Max Subgrid Length Scale= 3.402823E+38
Initial Layer Thickness= 3.402823E+38
Min Layer Thickness= 3.402823E+38
Max Layer Thickness= 3.402823E+38
Number of Layers= 5

--- MCCLDRN.f01 (steady flow) ---

Flow Title=Flow
Program Version=6.30
Number of Profiles= 1
Profile Names=F01pct
River Rch & RM=MCCLDRN,Main,3447
     723
Boundary for River Rch & Prof#=MCCLDRN,Main            , 1
Up Type= 0
Dn Type= 3
Dn Slope=0.02478
DSS Import GetInterval= 0
DSS Import GetPeak= 0
DSS Import FillOption= 0

--- MCCLDRN.g01 (geometry) ---

Geom Title=Geometry
Program Version=6.30

River Reach=MCCLDRN         ,Main
Reach XY= 30
1611133.65204969426993.1511172891611197.10668976427047.516782879
     1611176.142      427110.701     1611151.203       427479.24
     1611171.295      427498.459     1611248.166      427532.527
     1611290.097      427571.836     1611305.821      427627.743
     1611317.177      427750.913     1611422.876      427998.127
     1611442.094       428176.33     1611488.392      428251.455
     1611555.655      428324.833     1611578.242      428470.314
     1611551.679      428580.232     1611501.987      428695.874
     1611397.019      428785.471     1611343.907      428851.441
     1611296.579      429098.447      1611243.91      429132.567
     1611113.154      429163.711     1611057.737      429208.594
     1611049.121      429233.196     1611040.386      429556.462
     1610961.313      429711.203     1610963.016      429739.182
     1610993.185      429801.468     1610994.402      429836.747
     1610943.065      429964.481      1610918.51      430000.279

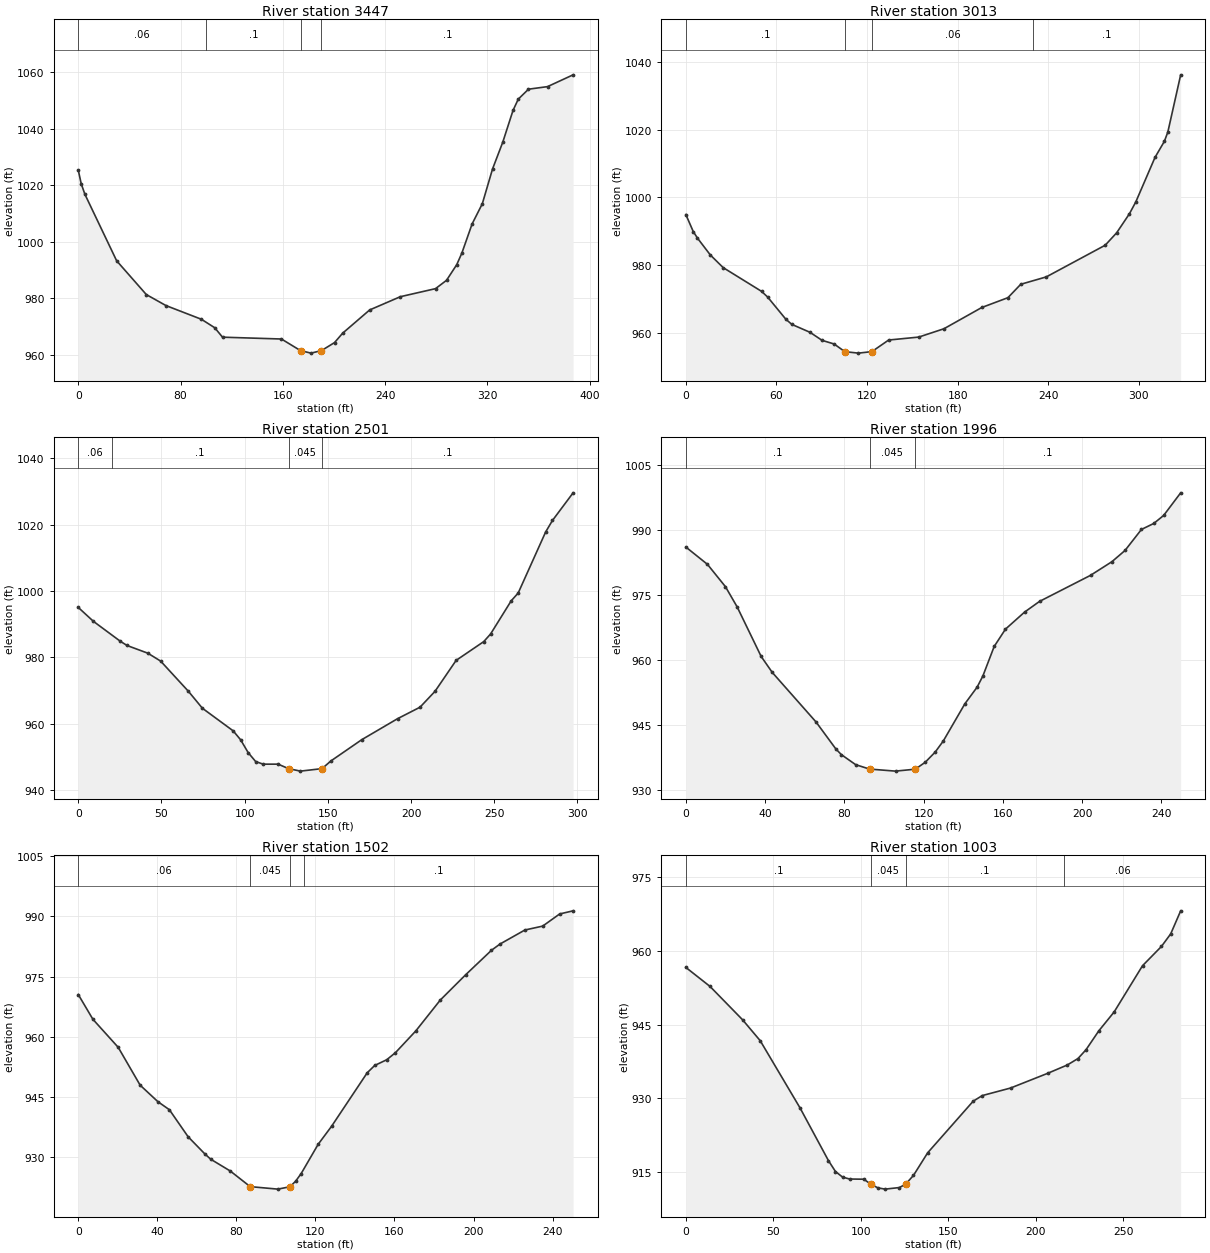
Type RM Length L Ch R = 1 ,3447    ,428.3,434.7,439.5
XS GIS Cut Line= 3
1611034.43275029427142.1388822151611197.51064245426986.694529818
1611359.00727977426978.396300806
#Sta/Elev= 30
       0 1025.35     2.3 1020.56     5.2 1016.81      30  993.28    53.2  981.32
    68.6  977.41    96.3  972.56   106.7  969.57   112.8  966.22   158.9  965.57
  173.82  961.46     182  960.57   190.2  961.46   200.4   964.3   206.8  967.65
   227.9  975.87   251.9  980.56   279.4  983.41     288  986.36     296  991.91
     300  996.01     308 1006.32     316 1013.49     324 1025.82     332  1035.3
     340 1046.53   344.1 1050.53   352.1 1054.06     367 1054.97     387 1059.15
#Mann= 4 ,-1,0
       0     .06       0     100      .1       0  173.82    .045       0
   190.2      .1       0
Bank Sta=173.82,190.2
XS Rating Curve= 0 ,0
Exp/Cntr(USF)=0,0
Exp/Cntr=0.3,0.1

Type RM Length L Ch R = 1 ,3013    ,513.8,511.4,506.2
XS GIS Cut Line= 4
1611044.76516003427464.0855597811611077.02080155427435.624699621
1611193.71032821427428.0351369111611352.14244977427373.010807268
#Sta/Elev= 30
       0   994.9     4.9  989.88     7.7  987.93    16.2  982.96    24.7  979.22
    50.1  972.21    54.1  970.55    66.2  963.97    70.2  962.43    82.2   960.1
    90.2  957.72    98.2  956.64   105.3  954.37   114.3  953.94   123.2 954.385
   134.3  957.81   154.2  958.68   170.9  961.14     196  967.43   213.3  970.33
   221.8  974.29   238.7  976.47   277.7  985.83   285.3   989.5   293.8  995.16
     298  998.65   310.7 1011.79   316.9 1016.54   319.2 1019.29   327.7  1036.2
#Mann= 4 ,-1,0
       0      .1       0   105.3    .045       0   123.2     .06       0
  229.95      .1       0
Bank Sta=105.3,123.2
XS Rating Curve= 0 ,0
Exp/Cntr(USF)=0,0
Exp/Cntr=0.3,0.1

Type RM Length L Ch R = 1 ,2501    ,507.3,505,502.7
XS GIS Cut Line= 4
1611235.05236434427894.1868444951611294.82017068427886.597281785
1611436.17577614427814.4964360461611512.07140324427794.573833933
#Sta/Elev= 30
       0  995.02     9.1  990.83    25.3  984.82    29.3  983.56    41.8  981.24
    49.5  978.86    66.2  969.75    74.6  964.65    93.1  957.84    97.6  955.13
   102.1  951.29   106.6   948.6   111.1  947.81   120.1  947.81   126.4  946.46
   133.5  945.71  146.48946.4608   151.9   948.8   170.4  955.19   191.9  961.51
   205.4  964.97   214.4  969.75   227.1  979.08   243.7  984.73   247.8  987.02
   260.2  997.02   264.4  999.37   280.9 1017.76     285 1021.23   297.4 1029.55
#Mann= 4 ,-1,0
       0     .06       0      20      .1       0   126.4    .045       0
  146.48      .1       0
Bank Sta=126.4,146.48
XS Rating Curve= 0 ,0
Exp/Cntr(USF)=0,0
Exp/Cntr=0.3,0.1

Type RM Length L Ch R = 1 ,1996    ,480.5,494.6,514.8
XS GIS Cut Line= 3
1611454.50633041428361.9045407611611508.26573294428333.443680601
1611659.00288119428219.600239959
#Sta/Elev= 30
       0   986.1    10.9   982.1      20  976.93    25.9  972.26      38  960.83
    43.6  957.14    65.7  945.69    75.7  939.46    78.5  938.14    85.7  935.83
   92.68934.8163   105.8  934.34   115.8  934.79   120.8  936.39   125.8  938.73
   129.9  941.29   140.8  949.89     147  953.75   149.9  956.33   155.6  963.14
   161.3  967.14   170.9  971.06   178.5  973.55   204.2  979.56     215  982.71
   221.6   985.3   229.9  990.16   236.1  991.54   241.1  993.39   249.7  998.62
#Mann= 3 ,-1,0
       0      .1       0   92.68    .045       0   115.8      .1       0
Bank Sta=92.68,115.8
XS Rating Curve= 0 ,0
Exp/Cntr(USF)=0,0
Exp/Cntr=0.3,0.1

Type RM Length L Ch R = 1 ,1502    ,491.2,498.1,499.6
XS GIS Cut Line= 4
1611377.62307629428684.5014171841611416.66403673428722.241012275
1611479.12957343428808.131125242 1611562.4169557428841.966624289
#Sta/Elev= 30
       0   970.5     7.4  964.34    20.2  957.35    31.3  947.92    40.3   943.8
    46.1   941.8    55.6  935.05    64.1  930.76      67  929.47    76.9  926.53
      87  922.63     101  922.01   107.1   922.6     110  923.99   112.8   925.9
   121.4  933.19   128.2  937.69   146.2     951     150  952.83   156.1  954.26
   160.5  956.02   170.8  961.44   183.2  969.14   196.1  975.47   209.1  981.54
   213.4  983.09     226  986.59     235  987.56   243.6  990.59   250.4  991.37
#Mann= 4 ,-1,0
       0     .06       0      87    .045       0   107.1     .06       0
   114.3      .1       0
Bank Sta=87,107.1
XS Rating Curve= 0 ,0
Exp/Cntr(USF)=0,0
Exp/Cntr=0.3,0.1

Type RM Length L Ch R = 1 ,1003    ,508.6,497,482.3
XS GIS Cut Line= 4
1611158.29808045429038.9931690031611192.03718206429082.372013936
 1611206.8585429429172.3854165681611308.31610181429263.883951289
#Sta/Elev= 30
       0  956.63    13.8  952.76    32.4  945.97    42.5   941.7    65.3  927.98
    81.5  917.27    85.5  915.05    89.6   913.9    93.6  913.52   101.7  913.48
   105.8  912.44   109.8  911.71   113.9  911.46     122  911.78  125.55912.4467
   130.1  914.26   138.2  918.86   164.2  929.37   169.4  930.52   185.6  932.06
   206.7  935.04     218  936.75   224.1  938.06   228.7  939.86     236   943.7
   244.8  947.57     261  956.98   271.8   960.9   277.1  963.46   282.8  968.16
#Mann= 4 ,-1,0
       0      .1       0   105.8    .045       0  125.55      .1       0
  216.18     .06       0
Bank Sta=105.8,125.55
XS Rating Curve= 0 ,0
Exp/Cntr(USF)=0,0
Exp/Cntr=0.3,0.1

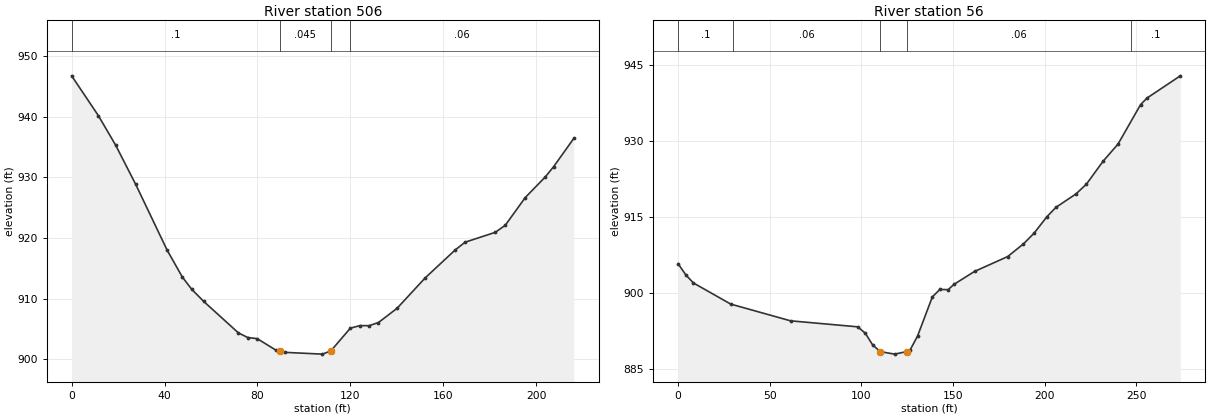
Type RM Length L Ch R = 1 ,506     ,448.4,450.3,450.4
XS GIS Cut Line= 3
1610940.62847657429530.0339760941611091.75564402429544.549014776
1611151.52345035429520.641892241
#Sta/Elev= 30
       0  946.76    11.5   940.2    18.9  935.36    27.5  928.93    41.1  918.03
    47.7  913.56    51.7  911.57    56.8  909.59    71.8  904.38    75.8  903.62
    79.9  903.43    87.9  901.55   89.51 901.397    91.9  901.17     108  900.88
   111.6901.4109     120  905.16   124.1  905.58   128.1  905.57   132.1  906.09
   140.1  908.43   152.2  913.44   165.1  918.04   169.4  919.33   182.4  920.96
   186.7  922.12   195.3  926.69   203.9  930.08   207.5  931.77   216.2  936.44
#Mann= 4 ,-1,0
       0      .1       0   89.51    .045       0   111.6      .1       0
     120     .06       0
Bank Sta=89.51,111.6
XS Rating Curve= 0 ,0
Exp/Cntr(USF)=0,0
Exp/Cntr=0.3,0.1

Type RM Length L Ch R = 1 ,56      ,,,
XS GIS Cut Line= 3
1610831.95949237 429930.048898551610976.50366286429958.404453528
1611078.86030034429883.711772123
#Sta/Elev= 30
       0  905.69     4.2  903.49     8.3  901.91    28.7  897.73    61.3  894.43
      98  893.24   102.1  891.98   106.1  889.68   110.2  888.35   118.1  887.85
   124.9  888.36   126.5  888.64   130.6   891.4   138.7  899.16   142.8  900.63
   147.3  900.58   150.5  901.63   161.7  904.18   179.8  907.12   188.4  909.62
   194.2  911.74   201.3  915.03   206.2  916.86   217.1   919.5   222.8  921.44
   231.9  925.97     240  929.33   252.3  937.12   255.8  938.42     274  942.82
#Mann= 5 ,-1,0
       0      .1       0      30     .06       0   110.2    .045       0
   124.9     .06       0   247.3      .1       0
Bank Sta=110.2,124.9
XS Rating Curve= 0 ,0
Exp/Cntr(USF)=0,0
Exp/Cntr=0.3,0.1
LCMann Table=0

Chan Stop Cuts=-1
Use User Specified Reach Order=0
Composite Channel Slope=5